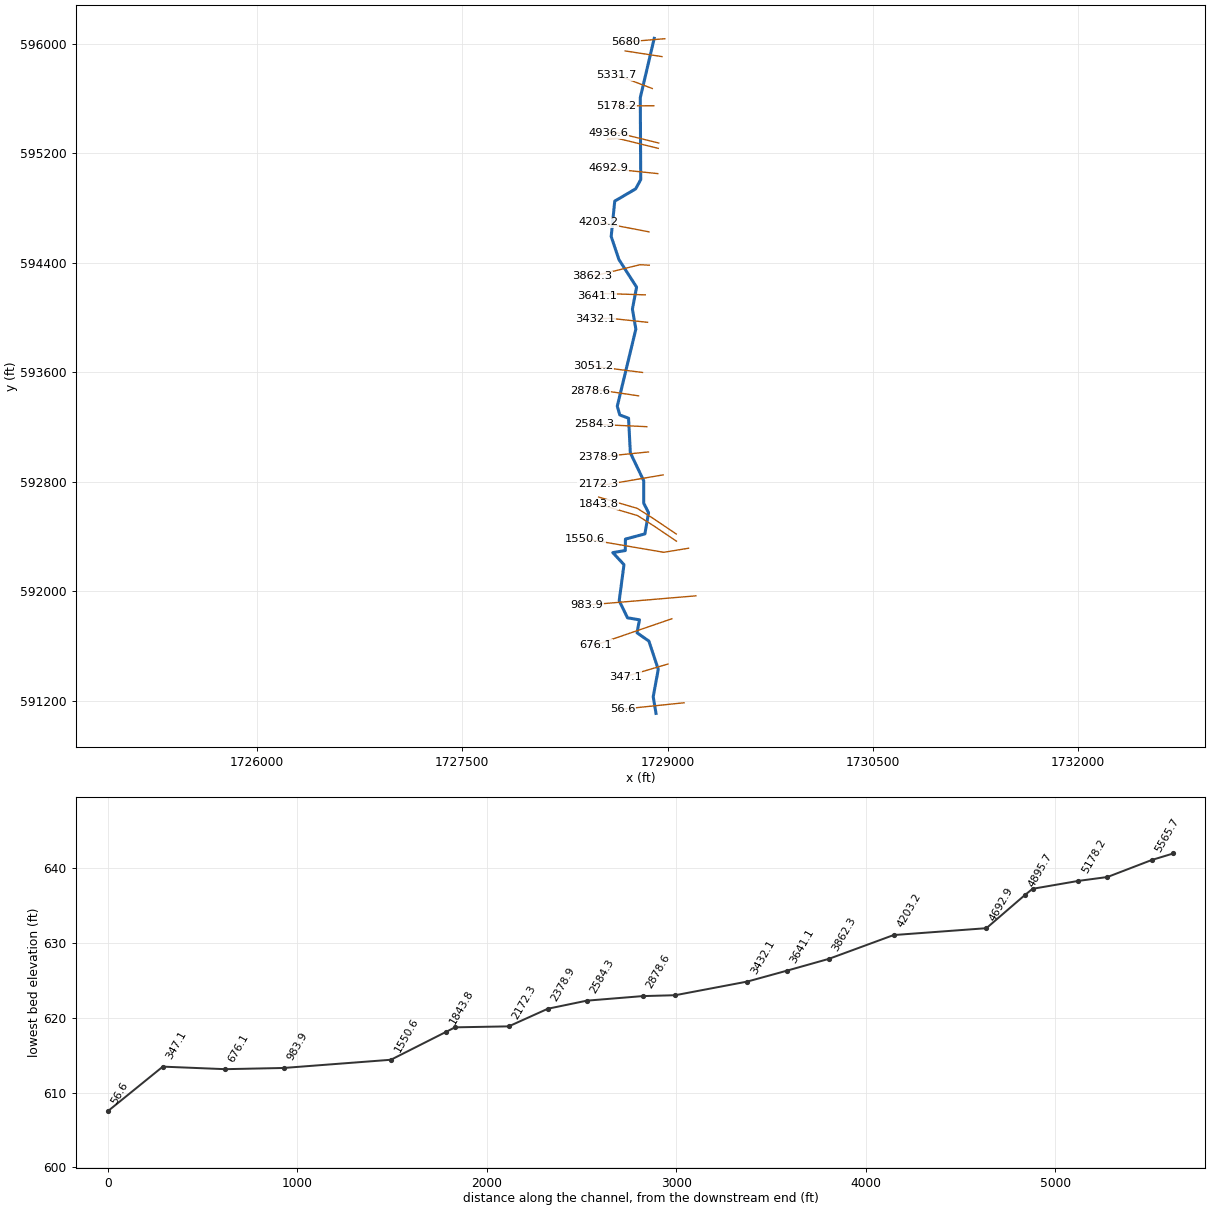
--- SprgValyBr.prj (project) ---

Proj Title=SprgValyBr
Current Plan=p01
Default Exp/Contr=0,0
English Units
Geom File=g01
Flow File=f01
Plan File=p01
BEGIN DESCRIPTION:
AMEC Environment & Infrastructure, 2013
Projection: NAD 1983 State Plane West Virginia South FIPS 4702 (US Feet)
Vertical Datum: NAVD 1988
END DESCRIPTION:
DSS Export Rating Curves= 0
DSS Export Rating Curve Sorted= 0
DSS Export Volume Flow Curves= 0
DXF OffsetX= 0
DXF OffsetY= 0
DXF ScaleX= 0
DXF ScaleY= 0

--- SprgValyBr.p01 (plan) ---

Plan Title=Floodplain
Program Version=4.00
Geom File=g01
Flow File=f01
K Sum by GR=0
Std Step Tol=0.01
Critical Tol=0.01
Num of Std Step Trials=20
Max Error Tol=0.3
Flow Tol Ratio=0.001
Split Flow NTrial=30
Split Flow Tol=0.02
Split Flow Ratio=0.02
Log Output Level=0
Friction Slope Method=1
Unsteady Friction Slope Method=2
Unsteady Bridges Friction Slope Method=1
Global Log Level=0
CheckData=False
Run HTab=0
Run UNet=0
Run PostProcess=0
UNET Theta=0
UNET Theta Warmup=0
UNET ZTol=0
UNET ZSATol=0
UNET MxIter=0
UNET MaxInSteps=0
UNET DtIC=0
UNET DtMin=0
UNET MaxCRTS=0
UNET WFStab=0
UNET SFStab=0
UNET WFX=0
UNET SFX=0
UNET DSS MLevel=0
UNET DZMax Abort=0
UNET Convert EG Bridges=0
UNET Use Existing IB Tables=0
UNET Froude Limit=0
UNET Froude Power=0
Write IC File=0
Echo Input=False
Echo Output=False
Write Detailed=0

--- SprgValyBr.f01 (steady flow) ---

Flow Title=USGS Regress. Eqn. (2010) - Western-Plateaus
Program Version=4.10
Number of Profiles= 1
Profile Names=P100yr
River Rch & RM=SprgValyBr,Main            ,5680
     900
River Rch & RM=SprgValyBr,Main            ,4692.9
     928
River Rch & RM=SprgValyBr,Main            ,4203.2
     936
River Rch & RM=SprgValyBr,Main            ,3862.3
    1008
River Rch & RM=SprgValyBr,Main            ,3051.2
    1017
River Rch & RM=SprgValyBr,Main            ,983.9
    1055
River Rch & RM=SprgValyBr,Main            ,56.6
    1069
Boundary for River Rch & Prof#=SprgValyBr,Main            , 1
Up Type= 0
Dn Type= 3
Dn Slope=0.0271
DSS Import GetInterval= 0
DSS Import GetPeak= 0
DSS Import FillOption= 0

--- SprgValyBr.g01 (geometry) ---

Geom Title=USGS 3m DEM
Program Version=4.10

River Reach=SprgValyBr      ,Main
Reach XY= 30
     1728902.277      596038.696     1728800.465      595605.392
      1728803.72      595006.433      1728766.66      594938.755
     1728613.833      594849.098     1728587.791      594590.852
     1728644.503      594421.607     1728773.338      594220.843
     1728742.956      594060.253     1728768.086      593913.686
     1728632.279      593350.617     1728650.725      593286.598
     1728714.744      593262.727     1728727.765      593009.906
     1728825.421      592805.913     1728825.421      592642.067
     1728860.995      592572.149     1728834.102      592417.458
     1728691.958       592379.48     1728690.873       592295.93
     1728599.727      592280.739     1728681.289      592192.856
     1728646.385      591929.176     1728707.149      591804.394
     1728794.393      591789.705     1728776.593      591694.801
     1728863.399      591634.038     1728931.758      591427.874
     1728894.866      591227.137     1728915.538      591105.998

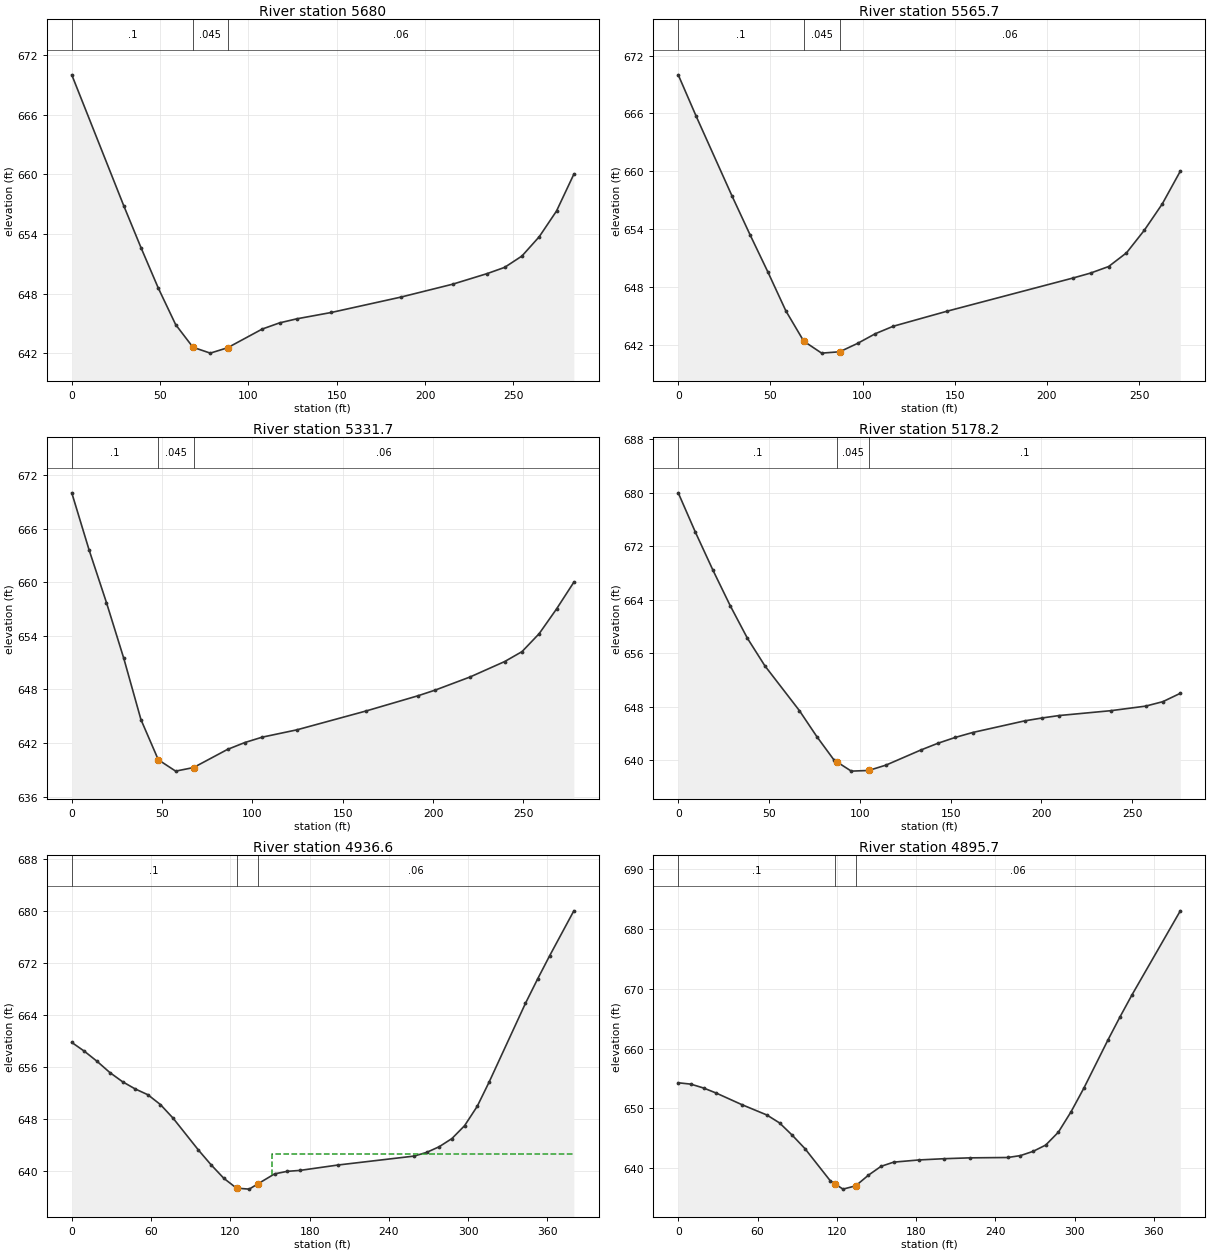
Type RM Length L Ch R = 1 ,5680    ,119.6,114.3,108.9
XS GIS Cut Line= 2
     1728980.099      596035.907     1728696.857       596012.48
#Sta/Elev= 20
       0     670    29.4  656.85    39.2  652.62      49  648.55    58.8  644.89
    68.6  642.61    78.4  642.02    88.2  642.56   107.8  644.44   117.6  645.06
   127.4  645.47     147  646.11   186.2  647.65   215.6  648.95   235.2  650.02
     245  650.64   254.8  651.78   264.6  653.72   274.4  656.31   284.2  660.01
#Mann= 3 , 0 , 0
       0      .1       0    68.6    .045       0    88.2     .06       0
Bank Sta=68.6,88.2
XS Rating Curve= 0 ,0
Exp/Cntr=0.3,0.1

Type RM Length L Ch R = 1 ,5565.7  ,238.2,233.9,229.3
XS GIS Cut Line= 2
     1728959.291      595905.168     1728690.086      595946.654
#Sta/Elev= 20
       0     670     9.7  665.72    29.2  657.43    38.9  653.44    48.6  649.57
    58.4  645.52    68.1  642.38    77.8  641.14    87.6  641.28    97.3  642.15
     107  643.16   116.7  643.93   145.9  645.49     214  648.92   223.7  649.44
   233.5  650.12   243.2  651.54   252.9  653.89   262.6  656.61   272.4  660.01
#Mann= 3 , 0 , 0
       0      .1       0    68.1    .045       0    87.6     .06       0
Bank Sta=68.1,87.6
XS Rating Curve= 0 ,0
Exp/Cntr=0.3,0.1

Type RM Length L Ch R = 1 ,5331.7  ,145.2,153.5,161.7
XS GIS Cut Line= 2
     1728888.121      595672.249     1728628.042       595770.16
#Sta/Elev= 21
       0     670     9.6   663.6    19.2  657.72    28.8  651.47    38.3  644.62
    47.9  640.13    57.5  638.86    67.4  639.26    86.2  641.29    95.8  642.06
   105.4  642.66   124.6  643.48   162.9  645.59   191.6  647.29   201.2  647.93
   220.4  649.39   239.6  651.12   249.2  652.23   258.7  654.24   268.3     657
   277.9     660
#Mann= 3 , 0 , 0
       0      .1       0    47.9    .045       0    67.4     .06       0
Bank Sta=47.9,67.4
XS Rating Curve= 0 ,0
Exp/Cntr=0.3,0.1

Type RM Length L Ch R = 1 ,5178.2  ,247.3,241.6,235.9
XS GIS Cut Line= 2
      1728899.75      595546.084     1728623.281      595545.205
#Sta/Elev= 24
       0     680     9.5  674.08    19.1  668.43    28.6  663.12    38.1  658.23
    47.7  654.11    66.7  647.41    76.3  643.52    85.8     640    87.3  639.74
    95.3  638.34   104.9  638.44   114.4  639.24   133.5  641.49     143  642.51
   152.5  643.38   162.1  644.12   190.7  645.86   200.2  646.29   209.7  646.66
   238.3  647.39   257.4  648.07   266.9  648.74   276.5  649.99
#Mann= 3 , 0 , 0
       0      .1       0    87.3    .045       0   104.9      .1       0
Bank Sta=87.3,104.9
XS Rating Curve= 0 ,0
Exp/Cntr=0.3,0.1

Type RM Length L Ch R = 1 ,4936.6  ,40.9,40.9,40.7
XS GIS Cut Line= 3
     1728935.343      595273.812     1728637.267      595346.932
     1728564.213      595345.523
#Sta/Elev= 30
       0   659.8     9.6  658.44    19.2  656.89    28.8  655.18    38.4  653.77
      48  652.66    57.6  651.77    67.1  650.26    76.7  648.17    95.9  643.27
   105.5     641   115.1  638.94   124.7  637.43   134.3  637.28   140.7  638.07
   153.5  639.62     163  640.01   172.6  640.15   201.4  640.98     259  642.35
   268.6  642.92   278.1  643.79   287.7  645.04   297.3  647.02   306.9     650
     316  653.77   343.4  665.81   352.6  669.55   361.7  673.11     380     680
#Mann= 3 , 0 , 0
       0      .1       0   124.7    .045       0   140.7     .06       0
#XS Ineff= 2 , 0
                          151.55          642.64
Permanent Ineff=
       F       F
Bank Sta=124.7,140.7
XS Rating Curve= 0 ,0
Exp/Cntr=0.3,0.1

Type RM Length L Ch R = 1 ,4895.7  ,199.5,202.8,206.2
XS GIS Cut Line= 3
      1728932.09      595234.738     1728634.014      595307.858
      1728560.96      595306.449
#Sta/Elev= 30
       0  654.26     9.6  654.03    19.2  653.38    28.8  652.53      48  650.61
    67.1  648.86    76.7  647.53    86.3  645.47    95.9  643.23   115.1  637.83
   118.7  637.31   124.7  636.44   134.3  636.99   143.9  638.77   153.5  640.26
     163  640.96   182.2  641.33   201.4  641.54   220.6  641.68   249.4  641.74
     259  642.06   268.6  642.77   278.1  643.82   287.7  645.98   297.3   649.4
   306.9  653.32   325.2  661.42   334.3  665.28   343.4  668.98     380  683.07
#Mann= 3 , 0 , 0
       0      .1       0   118.7    .045       0   134.3     .06       0
Bank Sta=118.7,134.3
XS Rating Curve= 0 ,0
Exp/Cntr=0.3,0.1

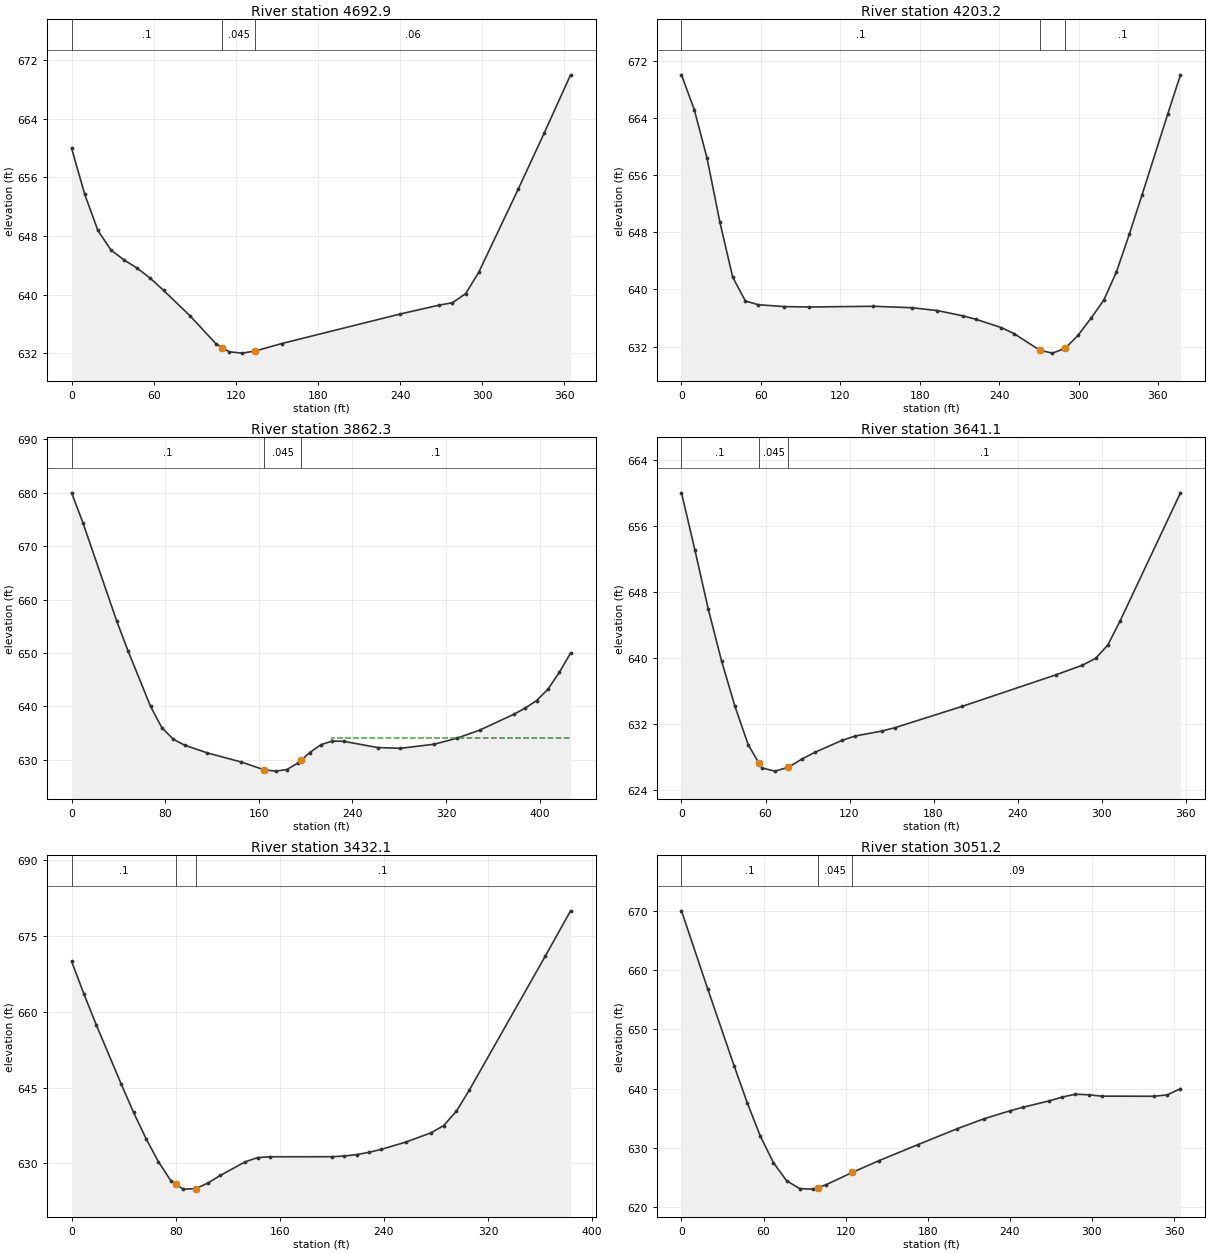
Type RM Length L Ch R = 1 ,4692.9  ,490.9,489.7,488.2
XS GIS Cut Line= 2
     1728928.445      595050.188     1728565.889      595087.942
#Sta/Elev= 23
       0  659.97     9.6  653.68    19.2  648.75    28.8  646.07    38.4  644.72
      48   643.6    57.6  642.21    67.2  640.57    86.3  637.14   105.5  633.28
   110.2  632.75   115.1  632.19   124.7  632.01   134.3  632.31   153.5  633.32
   239.8  637.34   268.6  638.57   278.2  638.89   287.8  640.12   297.4  643.04
   326.2  654.38   345.3  662.08   364.5     670
#Mann= 3 , 0 , 0
       0      .1       0   110.2    .045       0   134.3     .06       0
Bank Sta=110.2,134.3
XS Rating Curve= 0 ,0
Exp/Cntr=0.3,0.1

Type RM Length L Ch R = 1 ,4203.2  ,331.4,340.9,350.6
XS GIS Cut Line= 2
     1728864.117      594624.626     1728493.906      594695.754
#Sta/Elev= 27
       0     670     9.7   665.1    19.3  658.36      29  649.41    38.7   641.7
    48.3  638.38      58  637.86    77.3   637.6    96.7  637.54     145  637.64
     174  637.44   193.3  637.04   212.7   636.3   222.3  635.83   241.7  634.66
   251.3  633.81   270.8  631.49   280.3  631.09     290  631.77   299.6  633.59
   309.3  635.94     319  638.48   328.6  642.43   338.3  647.69     348  653.23
   367.3  664.47     377     670
#Mann= 3 , 0 , 0
       0      .1       0   270.8    .045       0     290      .1       0
Bank Sta=270.8,290
XS Rating Curve= 0 ,0
Exp/Cntr=0.3,0.1

Type RM Length L Ch R = 1 ,3862.3  ,227,221.1,214.9
XS GIS Cut Line= 3
     1728866.468      594380.914     1728799.024      594384.476
     1728450.257      594299.348
#Sta/Elev= 30
       0  679.96     9.6   674.4    38.6  655.96    48.2  650.41    67.5     640
    77.2  636.02    86.9  633.88    96.6  632.76     116  631.32   145.2   629.6
   164.6  628.16   174.3  627.91     184  628.21   193.7  629.46   196.2  629.95
   203.4  631.36   213.1  632.85   222.8  633.54   232.5  633.49   261.6  632.32
     281  632.18   310.1  632.95   329.5  634.08   348.9  635.59     378  638.54
   387.7   639.7   397.4   641.1   407.1  643.22   416.8  646.36   426.5     650
#Mann= 3 , 0 , 0
       0      .1       0   164.6    .045       0   196.2      .1       0
#XS Ineff= 2 , 0
                          222.54           634.1
Permanent Ineff=
       F       F
Bank Sta=164.6,196.2
XS Rating Curve= 0 ,0
Exp/Cntr=0.3,0.1

Type RM Length L Ch R = 1 ,3641.1  ,210.4,209,207
XS GIS Cut Line= 3
     1728836.792       594164.23     1728541.117      594173.673
     1728482.784       594157.27
#Sta/Elev= 23
       0     660     9.5  653.14    19.1  645.96    28.6  639.67    38.2  634.16
    47.7  629.51    55.3   627.3    57.3  626.72    66.8  626.33    76.3   626.8
    85.9  627.78    95.4  628.62   114.5  630.04   124.1  630.58   143.1  631.18
   152.7   631.6   200.4  634.16   267.2  637.97   286.3  639.14   295.8  639.97
   304.5  641.59   313.1  644.44   356.4     660
#Mann= 3 , 0 , 0
       0      .1       0    55.3    .045       0    76.3      .1       0
Bank Sta=55.3,76.3
XS Rating Curve= 0 ,0
Exp/Cntr=0.3,0.1

Type RM Length L Ch R = 1 ,3432.1  ,381.3,380.9,381
XS GIS Cut Line= 3
     1728853.728      593963.557     1728579.064      593993.085
     1728471.945      593988.667
#Sta/Elev= 28
       0  669.99     9.5  663.51      19  657.38    38.1   645.7    47.6  640.08
    57.2  634.88    66.7  630.31    76.2  626.55      80  625.88    85.7  624.87
    95.3  624.95   104.8  626.09   114.3  627.59   133.4  630.28   142.9  631.11
   152.4  631.28     200  631.29   209.6  631.43   219.1  631.71   228.6  632.17
   238.1  632.75   257.2  634.22   276.2  636.02     286  637.47   295.7   640.3
   305.5  644.41     364  671.01   383.5     680
#Mann= 3 , 0 , 0
       0      .1       0      80    .045       0    95.3      .1       0
Bank Sta=80,95.3
XS Rating Curve= 0 ,0
Exp/Cntr=0.3,0.1

Type RM Length L Ch R = 1 ,3051.2  ,172.8,172.6,172.3
XS GIS Cut Line= 2
     1728816.407      593597.269     1728454.536      593642.846
#Sta/Elev= 26
       0     670    19.2  656.81    38.4   643.9      48  637.65    57.6  631.99
    67.2  627.51    76.8  624.46    86.4  623.12      96  623.04    99.5623.3062
   105.6  623.77   124.8  625.86     144  627.81   172.8  630.55   201.6  633.24
   220.8  634.89     240  636.25   249.6  636.86   268.8  637.93   278.4  638.58
   287.9  639.06   297.5  638.96   307.1  638.73   345.5  638.71   355.1  638.95
   364.7     640
#Mann= 3 , 0 , 0
       0      .1       0    99.5    .045       0   124.8     .09       0
Bank Sta=99.5,124.8
XS Rating Curve= 0 ,0
Exp/Cntr=0.3,0.1

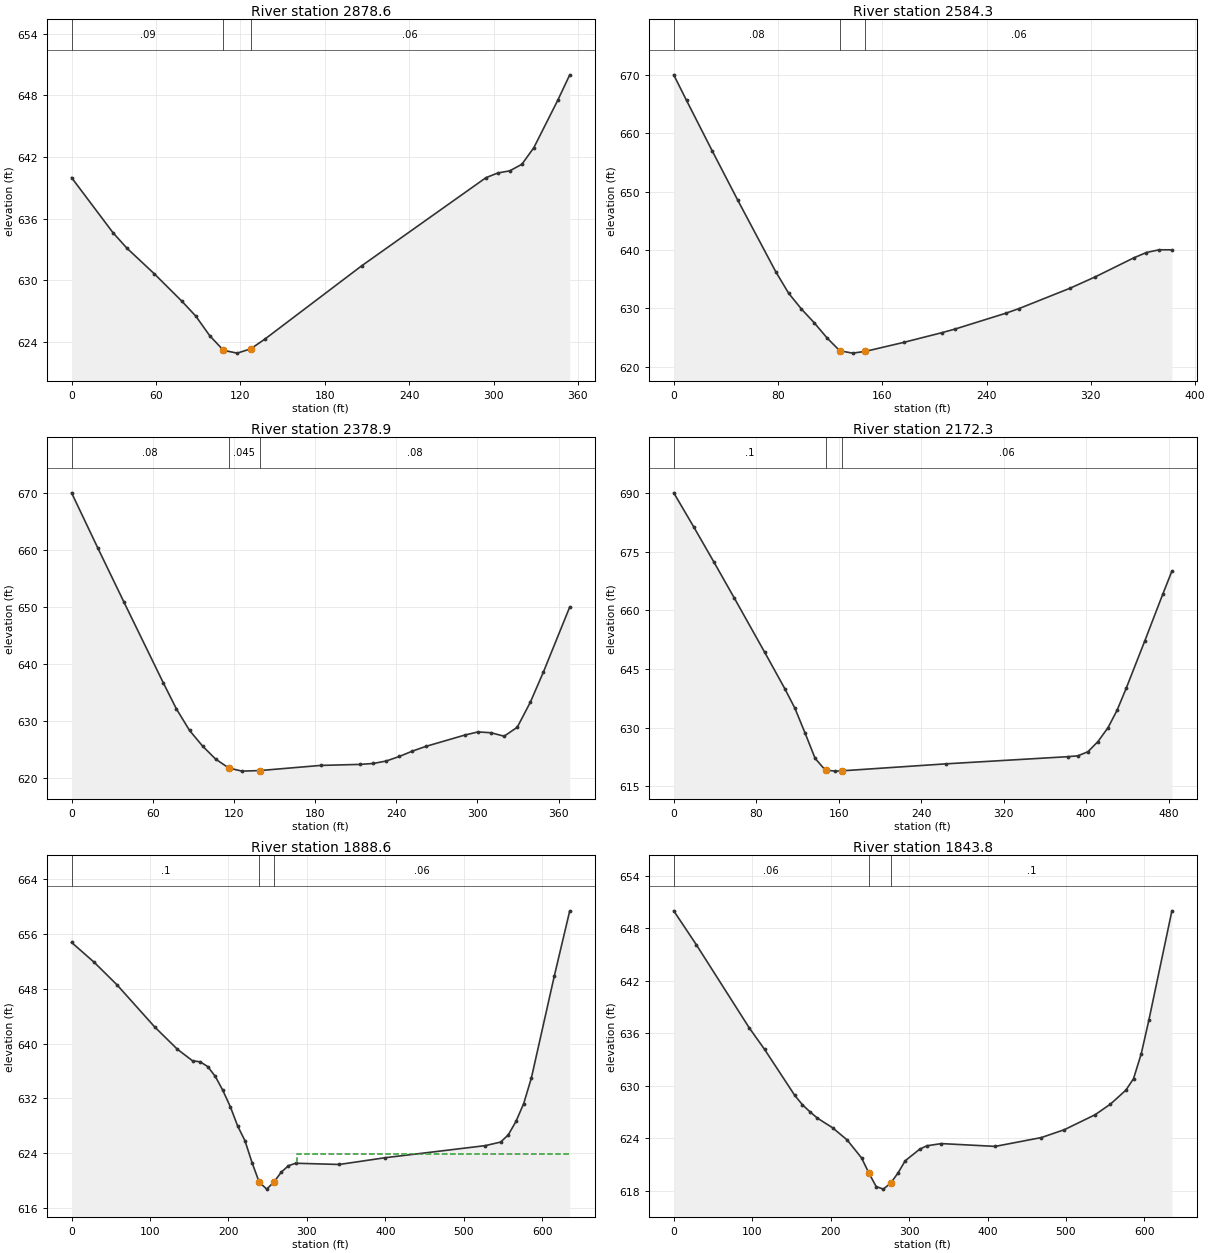
Type RM Length L Ch R = 1 ,2878.6  ,293,294.3,294.1
XS GIS Cut Line= 3
     1728787.901      593426.364     1728496.478      593469.586
     1728437.091      593464.775
#Sta/Elev= 19
       0     640    29.5  634.63    39.3  633.14    58.9  630.63    78.6  627.95
    88.4  626.51    98.2  624.62     108  623.19   117.8  622.92   127.4  623.34
   137.5  624.29   206.2  631.41   294.6  639.99   303.1  640.45   311.6  640.66
   320.2   641.3   328.7  642.92   345.7  647.53   354.2     650
#Mann= 3 , 0 , 0
       0     .09       0     108    .045       0   127.4     .06       0
Bank Sta=108,127.4
XS Rating Curve= 0 ,0
Exp/Cntr=0.3,0.1

Type RM Length L Ch R = 1 ,2584.3  ,202.1,205.4,208.7
XS GIS Cut Line= 2
     1728848.592      593200.912     1728466.819      593218.512
#Sta/Elev= 24
       0     670     9.8  665.62    29.4  657.02      49  648.57    78.4  636.21
    88.2  632.56      98  629.86   107.8  627.51   117.6  624.92   127.4  622.71
   127.9  622.69   137.2  622.31     147  622.61   176.4  624.15   205.8  625.82
   215.6  626.42   254.8  629.15   264.6  629.92   303.8  633.41   323.4  635.38
   352.8  638.62   362.6  639.55   372.4  640.02   382.2  640.01
#Mann= 3 , 0 , 0
       0     .08       0   127.9    .045       0     147     .06       0
Bank Sta=127.9,147
XS Rating Curve= 0 ,0
Exp/Cntr=0.3,0.1

Type RM Length L Ch R = 1 ,2378.9  ,205.8,206.5,207.7
XS GIS Cut Line= 2
     1728860.295      593016.476     1728493.906      592979.373
#Sta/Elev= 26
       0  670.01    19.4  660.34    38.8  650.82    67.8  636.71    77.5  632.14
    87.2  628.37    96.9  625.61   106.6  623.32   116.3  621.77     126  621.23
   139.2  621.33   184.1  622.23   213.2  622.41   222.9  622.57   232.6     623
   242.3   623.8     252  624.74   261.7  625.55   290.7  627.55   300.4   628.1
   310.1  627.96   319.8  627.35   329.5  628.92   339.2  633.33   348.9  638.64
   368.3     650
#Mann= 3 , 0 , 0
       0     .08       0   116.3    .045       0   139.2     .08       0
Bank Sta=116.3,139.2
XS Rating Curve= 0 ,0
Exp/Cntr=0.3,0.1

Type RM Length L Ch R = 1 ,2172.3  ,298.9,283.7,266.3
XS GIS Cut Line= 3
     1728968.186      592848.777     1728552.987       592778.04
     1728491.141      592780.805
#Sta/Elev= 24
       0     690    19.6   681.2    39.2   672.2    58.8  663.08    88.2  649.25
   107.7  639.95   117.5  634.95   127.3  628.64   137.1  622.14   146.9  619.15
   147.7  619.13   156.7  618.87   162.7  618.94   264.5  620.74     382  622.56
   391.8  622.78   401.6  623.81   411.4  626.43   421.2     630     430  634.47
   438.9  640.13   456.6  652.01   474.2  664.07   483.1  669.99
#Mann= 3 , 0 , 0
       0      .1       0   147.7    .045       0   162.7     .06       0
Bank Sta=147.7,162.7
XS Rating Curve= 0 ,0
Exp/Cntr=0.3,0.1

Type RM Length L Ch R = 1 ,1888.6  ,45.6,44.8,45.4
XS GIS Cut Line= 4
     1729063.226      592416.789     1728895.364      592530.028
     1728778.136      592604.258     1728496.136      592686.694
#Sta/Elev= 30
       0  654.76    28.9  651.85    57.8  648.58   106.1   642.4     135  639.15
   154.3  637.47   163.9  637.33   173.6  636.63   183.2   635.2   192.8  633.16
   202.5  630.73   211.7  627.96     221  625.81   230.2  622.56   239.1  619.78
   248.7  618.74     258  619.78   267.2  621.21   276.5  622.16   285.7  622.52
   341.2  622.34     400  623.33   527.3  625.09   546.9  625.61   556.7  626.67
   566.5  628.63   576.3  631.23   586.1  634.97   615.4  649.89     635  659.37
#Mann= 3 , 0 , 0
       0      .1       0   239.1    .045       0     258     .06       0
#XS Ineff= 2 , 0
                           286.9          623.87
Permanent Ineff=
       F       F
Bank Sta=239.1,258
XS Rating Curve= 0 ,0
Exp/Cntr=0.3,0.1

Type RM Length L Ch R = 1 ,1843.8  ,281.2,293.2,301.8
XS GIS Cut Line= 4
     1729064.771      592364.273     1728896.909      592477.512
     1728779.681      592551.741     1728497.682      592634.177
#Sta/Elev= 30
       0     650    28.9  646.11    96.4  636.59   115.7  634.16   154.3  628.88
   163.9  627.83   173.6  627.01   183.2  626.28   202.5  625.18     221  623.79
   239.5  621.72   248.7  620.01     258  618.46   267.2  618.16   276.5  618.85
   285.7  619.98     295   621.4   313.5  622.73   322.7  623.12   341.2  623.37
   409.8  623.05   468.6  624.06   497.9  624.96   537.1  626.67   556.7  627.89
   576.3  629.48   586.1   630.8   595.9  633.64   605.7  637.52     635     650
#Mann= 3 , 0 , 0
       0     .06       0   248.7    .045       0   276.5      .1       0
Bank Sta=248.7,276.5
XS Rating Curve= 0 ,0
Exp/Cntr=0.3,0.1

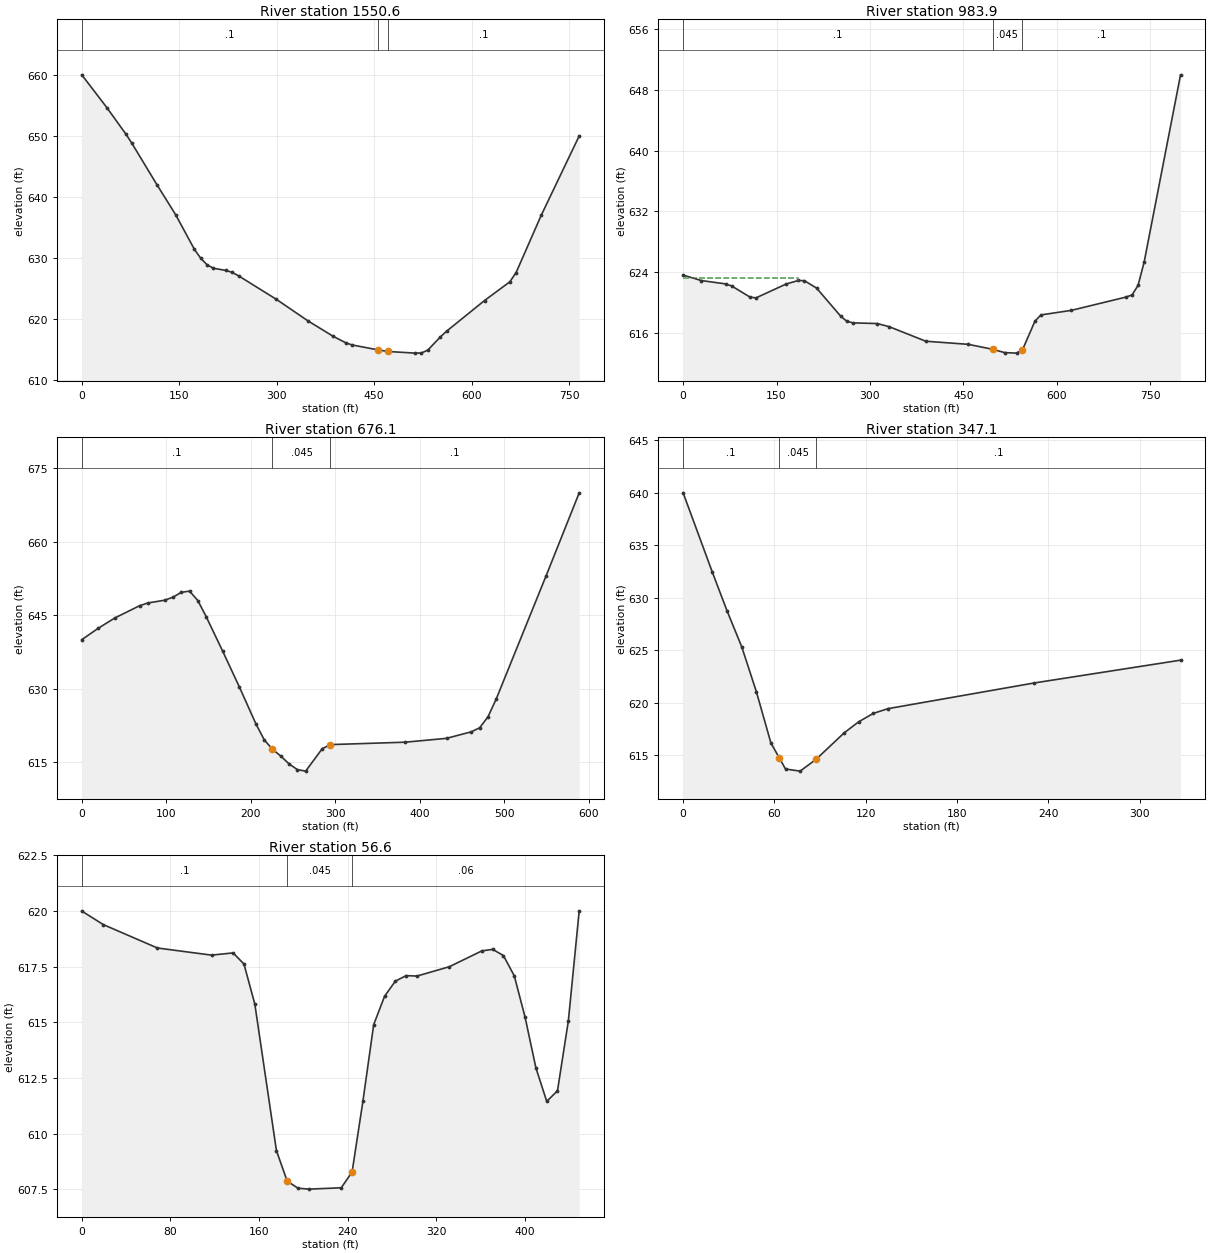
Type RM Length L Ch R = 1 ,1550.6  ,515,566.7,558.6
XS GIS Cut Line= 3
     1729153.354      592312.864     1728972.891      592282.927
     1728398.664      592381.156
#Sta/Elev= 30
       0     660    38.5  654.64    67.4  650.36      77   648.8   115.5  642.02
   144.4  637.09   173.3  631.41   182.9  629.96   192.6   628.9   202.4  628.31
   221.8  627.95   231.5  627.63   241.2  627.07   299.4  623.22     348  619.69
   386.8  617.16   406.2   616.1     416  615.74   456.5  614.92   471.5  614.67
     513   614.4   522.8  614.43   532.5  614.89   551.9  617.06   561.6  618.01
   619.8  623.02   658.7  626.08   668.4   627.6   707.2  637.02   765.5  649.99
#Mann= 3 , 0 , 0
       0      .1       0   456.5    .045       0   471.5      .1       0
Bank Sta=456.5,471.5
XS Rating Curve= 0 ,0
Exp/Cntr=0.3,0.1

Type RM Length L Ch R = 1 ,983.9   ,297.5,307.8,330
XS GIS Cut Line= 2
     1729206.895      591964.972     1728410.842      591897.732
#Sta/Elev= 30
       0  623.59    29.2  622.87    68.2  622.43    77.9  622.16   107.2   620.7
   116.9  620.58   165.6  622.42   185.1  622.88   194.8  622.85   214.3  621.88
   253.3  618.15     263   617.5   272.8  617.29   311.8   617.2   331.2  616.78
   389.7  614.87   457.9  614.46   496.9  613.81   516.4  613.37   535.8   613.3
   544.2  613.76   545.6  613.84   565.1  617.52   574.8  618.34   623.5  618.94
   711.2  620.69     721  620.97   730.7  622.24   740.4  625.29   798.9     650
#Mann= 3 , 0 , 0
       0      .1       0   496.9    .045       0   544.2      .1       0
#XS Ineff= 2 , 0
          184.79  623.22
Permanent Ineff=
       F       F
Bank Sta=496.9,544.2
XS Rating Curve= 0 ,0
Exp/Cntr=0.3,0.1

Type RM Length L Ch R = 1 ,676.1   ,333.3,329,328.2
XS GIS Cut Line= 2
     1729031.579      591797.454     1728474.641      591606.362
#Sta/Elev= 30
       0     640    19.6  642.34    39.2  644.44    68.7  646.96    78.5   647.5
    98.1  648.06     108  648.68   117.8  649.67   127.6  649.92   137.4  647.98
   147.2  644.72   166.8  637.64   186.5  630.35   206.1   622.8   215.9  619.56
   225.7   617.6   235.5  616.23   245.3  614.63   255.2  613.45     265  613.14
   284.6  617.72   294.4  618.56   382.7  619.05   431.8  619.84   461.2  621.18
     471     622   480.9  624.26   490.7  627.93   549.6  653.04   588.8     670
#Mann= 3 , 0 , 0
       0      .1       0   225.7    .045       0   294.4      .1       0
Bank Sta=225.7,294.4
XS Rating Curve= 0 ,0
Exp/Cntr=0.3,0.1

Type RM Length L Ch R = 1 ,347.1   ,294.5,290.5,286.1
XS GIS Cut Line= 2
     1729003.495      591466.766     1728689.915       591374.31
#Sta/Elev= 16
       0  639.99    19.2  632.43    28.8  628.77    38.5  625.33    48.1  621.06
    57.7  616.16    63.1 614.765    67.3  613.68    76.9  613.48    87.4  614.61
   105.8  617.12   115.4  618.18     125  618.98   134.6  619.43   230.8  621.88
   326.9  624.05
#Mann= 3 , 0 , 0
       0      .1       0    63.1    .045       0    87.4      .1       0
Bank Sta=63.1,87.4
XS Rating Curve= 0 ,0
Exp/Cntr=0.3,0.1

Type RM Length L Ch R = 1 ,56.6    ,53.4,56.6,59.7
XS GIS Cut Line= 2
     1729120.604      591183.555     1728674.037      591137.308
#Sta/Elev= 30
       0     620    19.5  619.39    68.3  618.34   117.1  618.02   136.6  618.12
   146.4  617.62   156.2  615.82   175.7  609.24   185.4  607.87   195.2  607.55
     205  607.51   234.2  607.57     244  608.28   253.8  611.47   263.5   614.9
   273.3  616.17     283  616.85   292.8   617.1   302.6  617.08   331.8   617.5
   361.1  618.21   370.9  618.28   380.6     618   390.4  617.09   400.2  615.22
   409.9  612.96   419.7  611.45   429.4  611.93   439.2  615.06     449  620.01
#Mann= 3 , 0 , 0
       0      .1       0   185.4    .045       0     244     .06       0
Bank Sta=185.4,244
XS Rating Curve= 0 ,0
Exp/Cntr=0.3,0.1

Chan Stop Cuts=-1
Use User Specified Reach Order=0
Composite Channel Slope=5